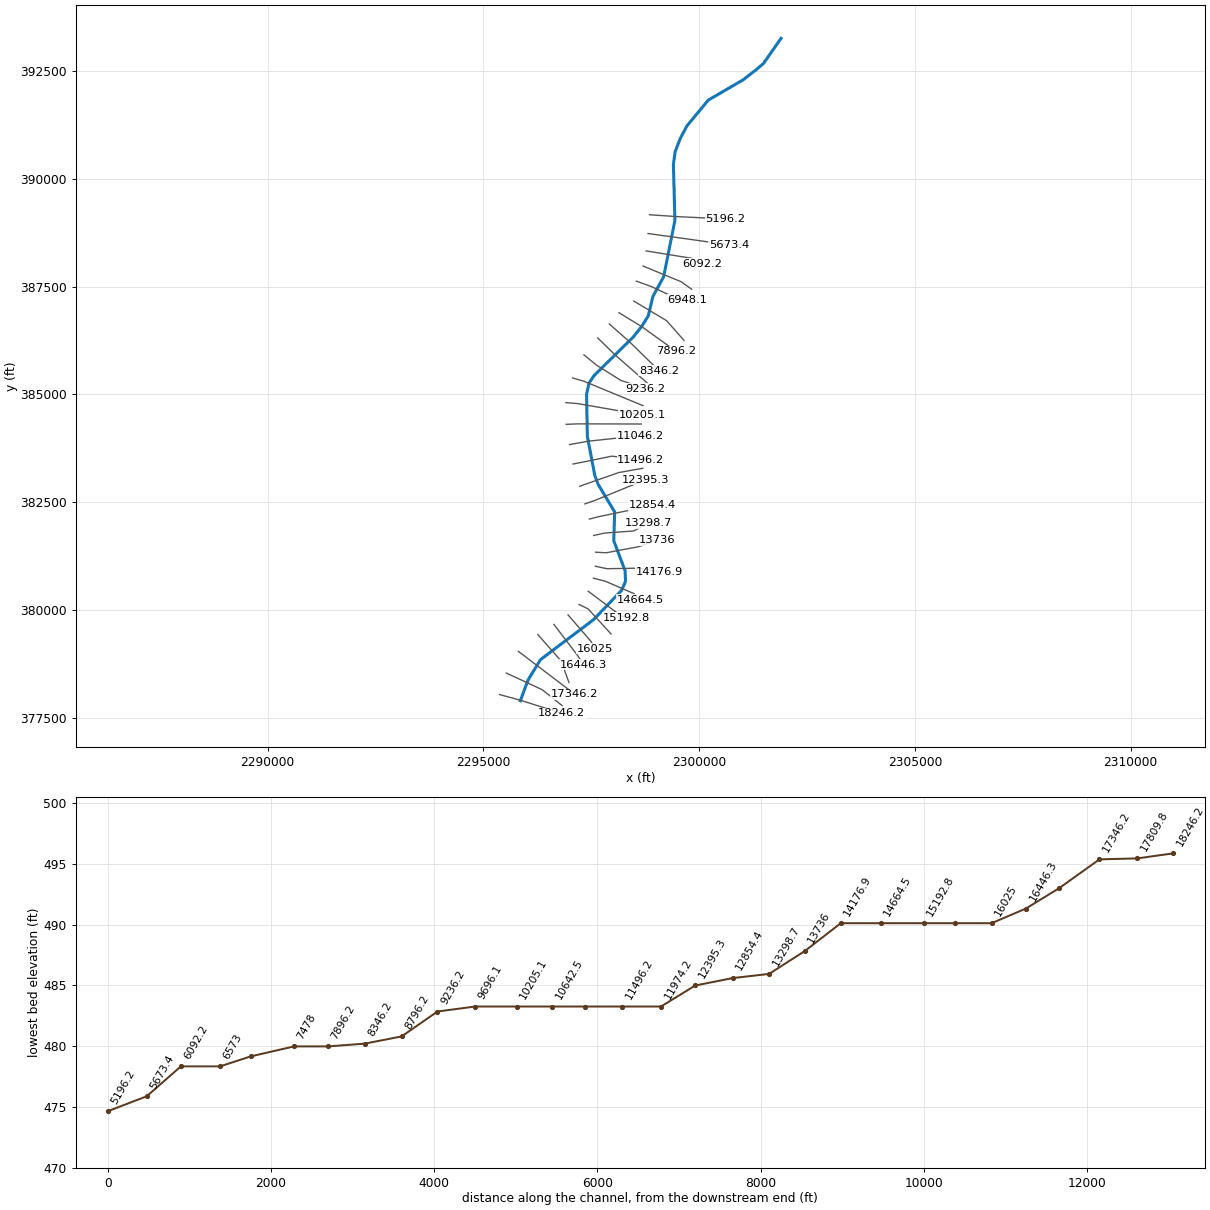
--- CACAPONRIV.prj (project) ---

Proj Title=CACAPONRIV
Current Plan=p01
Default Exp/Contr=0,0
English Units
Geom File=g01
Flow File=f01
Plan File=p01
BEGIN DESCRIPTION:
END DESCRIPTION:
DSS Export Rating Curves= 0
DSS Export Rating Curve Sorted= 0
DSS Export Volume Flow Curves= 0
DXF OffsetX= 0
DXF OffsetY= 0
DXF ScaleX= 0
DXF ScaleY= 0

--- CACAPONRIV.p01 (plan) ---

Plan Title=Floodplain
Program Version=4.00
Geom File=g01
Flow File=f01
K Sum by GR=0
Std Step Tol=0.01
Critical Tol=0.01
Num of Std Step Trials=20
Max Error Tol=0.3
Flow Tol Ratio=0.001
Split Flow NTrial=30
Split Flow Tol=0.02
Split Flow Ratio=0.02
Log Output Level=0
Friction Slope Method=1
Unsteady Friction Slope Method=2
Unsteady Bridges Friction Slope Method=1
Global Log Level=0
CheckData=False
Run HTab=0
Run UNet=0
Run PostProcess=0
UNET Theta=0
UNET Theta Warmup=0
UNET ZTol=0
UNET ZSATol=0
UNET MxIter=0
UNET MaxInSteps=0
UNET DtIC=0
UNET DtMin=0
UNET MaxCRTS=0
UNET WFStab=0
UNET SFStab=0
UNET WFX=0
UNET SFX=0
UNET DSS MLevel=0
UNET DZMax Abort=0
UNET Convert EG Bridges=0
UNET Use Existing IB Tables=0
UNET Froude Limit=0
UNET Froude Power=0
Write IC File=0
Echo Input=False
Echo Output=False
Write Detailed=0

--- CACAPONRIV.f01 (steady flow) ---

Flow Title=NFF Regression Equation
Program Version=4.10
Number of Profiles= 1
Profile Names=P100yr
River Rch & RM=CACAPONRIV,Main            ,18246.2
75476.02
River Rch & RM=CACAPONRIV,Main            ,244.8
75951.75
Boundary for River Rch & Prof#=CACAPONRIV,Main            , 1
Up Type= 0
Dn Type= 1
Dn Known WS=493.8
Set Internal Change=CACAPONRIV      ,Main            ,18246.2 , 1 , 3 ,526.8
DSS Import GetInterval= 0
DSS Import GetPeak= 0
DSS Import FillOption= 0

--- CACAPONRIV.g01 (geometry) ---

Geom Title=USGS 10m DEM
Program Version=4.10

River Reach=CACAPONRIV      ,Main
Reach XY= 30
     2295856.951      377907.986     2296032.298       378383.68
     2296322.229      378857.638     2297556.604      379788.194
     2298198.965      380458.333     2298294.451      380670.138
     2298284.034      380918.402     2298021.882      381609.375
     2298042.715      382279.513     2297657.298      382921.875
     2297580.909      383130.208     2297409.034      384032.986
     2297391.673      385005.208     2297447.229      385262.152
     2297565.284      385439.236     2298469.798      386328.124
     2298669.451      386576.388     2298820.492      386819.444
     2298928.131      387269.096     2299178.131       387727.43
     2299438.548      389032.985     2299403.826       390329.86
     2299445.493      390630.208      2299567.02      390939.235
     2299718.062      391222.221     2300212.854      391819.444
     2301013.201      392284.722     2301323.965      392524.305
     2301490.631      392666.666     2301898.618      393249.999

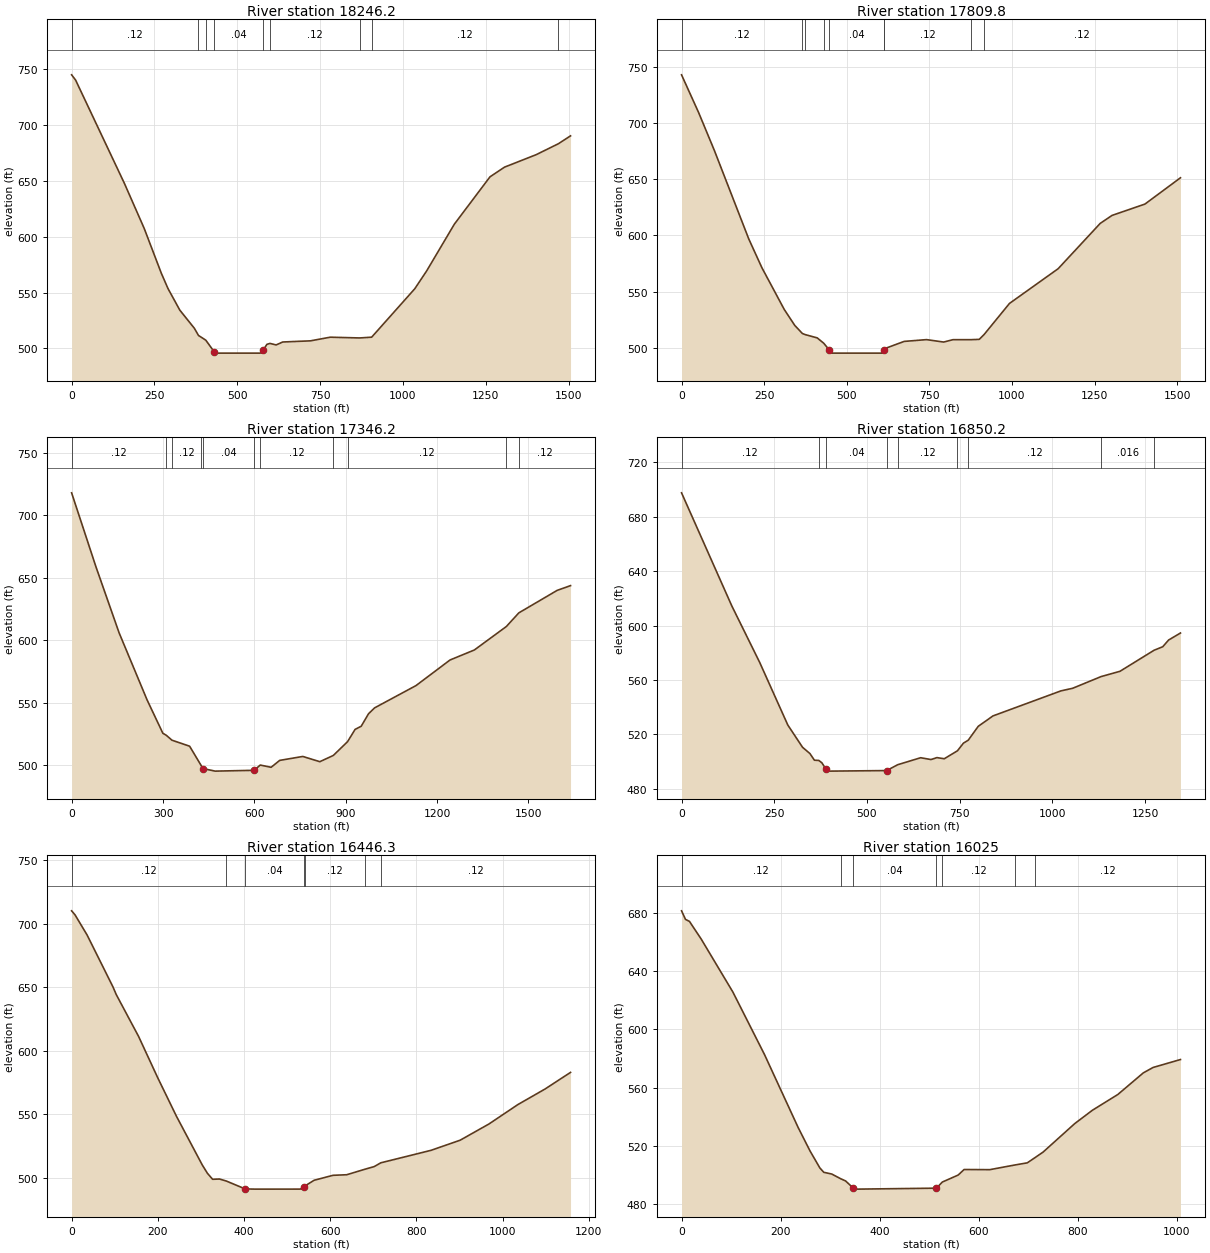
Type RM Length L Ch R = 1 ,18246.2 ,440.1,436.4,433.5
XS GIS Cut Line= 3
     2295375.413      378049.679     2295859.582      377917.633
      2296816.56      377613.662
#Sta/Elev= 30
       0  744.93      12  740.28   159.3  647.81   219.1  607.49   270.8  567.34
   290.8  553.72   326.6  534.33   370.4  518.14     383511.6635  405.11507.4169
   430.2  497.12   442.1  495.85   569.6  495.85   577.6  498.27   589.5  503.71
  598.81504.5468   617.4  503.19   637.3  505.81     721  506.85   780.8  510.11
  869.49509.4354  905.73510.1353  1035.8  553.44  1071.6  569.37  1155.3  611.26
  1262.9  653.64  1306.7   662.3  1402.4  673.48 1469.26683.2435    1506  690.32
#Mann= 9 ,-1 , 0
       0     .12       0     383    .016       0  405.11     .12       0
   430.2     .04       0   577.6     .04       0  598.81     .12       0
  869.49    .016       0  905.73     .12       0 1469.26    .016       0
Bank Sta=430.2,577.6
XS Rating Curve= 0 ,0
Exp/Cntr=0.3,0.1

Type RM Length L Ch R = 1 ,17809.8 ,468.5,463.6,458.8
XS GIS Cut Line= 3
      2295530.56      378548.366     2296362.171      378162.423
     2296825.712      377792.632
#Sta/Elev= 30
       0  742.73    51.8  709.13    99.6  675.33   203.3  596.98   243.2  571.32
   310.9   534.2   342.8     520  365.76512.8574   374.6 511.854   410.6  508.98
  430.35504.1979   446.4   498.5   454.4  495.44   605.9  495.44   613.9  497.79
  613.91497.7951   617.8  499.78   673.6  505.85   741.4  507.44   793.2  505.28
   821.1  507.38  877.25   507.4   900.9  507.68  915.76512.0448   992.4   539.6
  1139.7  570.46    1267  610.73  1302.8  617.82  1402.3  627.88  1509.8  651.25
#Mann= 9 ,-1 , 0
       0     .12       0  365.76     .06       0   374.6    .016       0
  430.35     .04       0   446.4     .04       0   613.9     .04       0
  613.91     .12       0  877.25    .016       0  915.76     .12       0
Bank Sta=446.4,613.9
XS Rating Curve= 0 ,0
Exp/Cntr=0.3,0.1

Type RM Length L Ch R = 1 ,17346.2 ,500.4,496,491.5
XS GIS Cut Line= 3
     2295811.136      379049.699     2296227.928      378733.383
     2297115.852      378059.158
#Sta/Elev= 30
       0  718.04    79.9  658.86   155.8  606.11   247.6  552.46   299.6  525.66
  310.74524.0481  329.64520.0955   387.4  515.31  425.51 499.789   431.4  497.41
   471.3  495.36   599.2  496.01  619.37500.2149   655.1  498.42   683.1  503.94
     759   507.1   814.9  502.91  859.31507.9087  905.97518.9219   930.8  528.76
   950.8  531.26   974.8  541.24   994.8  545.98  1130.6  563.78  1242.5  584.29
  1322.4   592.3  1427.4611.0745 1468.45622.0015  1594.2  639.99  1638.1  643.79
#Mann= 11 ,-1 , 0
       0     .12       0  310.74     .08       0  329.64     .12       0
  425.51     .04       0   431.4     .04       0   599.2     .04       0
  619.37     .12       0  859.31    .016       0  905.97     .12       0
  1427.4    .016       0 1468.45     .12       0
Bank Sta=431.4,599.2
XS Rating Curve= 0 ,0
Exp/Cntr=0.3,0.1

Type RM Length L Ch R = 1 ,16850.2 ,405.5,403.9,402.3
XS GIS Cut Line= 3
     2296262.159      379438.655     2296804.879      378823.882
     2296981.962       378329.09
#Sta/Elev= 30
       0  697.59   135.4  614.54     211  572.77   286.6  526.88   326.4  510.49
   346.3  505.88   358.3  501.01  370.18500.8294   378.2  499.19   390.1  494.26
   398.1  492.98   553.3  493.38  582.83497.6794   644.9  502.83   672.8  501.49
   688.7  502.92   708.6  502.08  744.13507.9367   760.3  513.56  773.17515.7024
   800.2  525.92     840  533.58  1023.1  551.97    1055  553.91 1131.66562.4991
  1182.4  566.37 1274.55 581.868  1297.8  584.43  1313.7  589.38  1345.6  594.52
#Mann= 9 ,-1 , 0
       0     .12       0  370.18     .04       0   390.1     .04       0
   553.3     .04       0  582.83     .12       0  744.13    .016       0
  773.17     .12       0 1131.66    .016       0 1274.55     .12       0
Bank Sta=390.1,553.3
XS Rating Curve= 0 ,0
Exp/Cntr=0.3,0.1

Type RM Length L Ch R = 1 ,16446.3 ,419.9,421.3,422.7
XS GIS Cut Line= 3
      2296635.57      379673.185     2297179.879      378959.298
     2297320.504      378740.548
#Sta/Elev= 30
       0  710.01       8  706.82    35.9  691.04    95.8  650.35   103.7  644.14
   155.6   611.2   199.5  579.08   243.4  548.51   303.2  510.31   315.2  503.75
   327.2  499.05   343.1  499.26  358.94497.6868     403  491.46   426.9  491.32
   530.6  491.34   538.6  492.68  541.93493.8955   562.6  498.26   606.5  502.18
   638.4  502.62   681.9 507.072   702.2  509.03  717.54511.9958   833.9  521.79
   901.7  529.77   968.6  542.53  1035.6  557.76  1098.7     570  1157.8  583.05
#Mann= 7 ,-1 , 0
       0     .12       0  358.94     .04       0     403     .04       0
   538.6     .04       0  541.93     .12       0   681.9    .016       0
  717.54     .12       0
Bank Sta=403,538.6
XS Rating Curve= 0 ,0
Exp/Cntr=0.3,0.1

Type RM Length L Ch R = 1 ,16025   ,451.1,451.7,452.3
XS GIS Cut Line= 3
     2296961.879      379894.484     2297487.171      379288.812
     2297591.337      379111.729
#Sta/Elev= 30
       0  681.58       8  675.69      16   674.3    39.9  662.03   103.7  625.67
   167.5  582.68   235.3  532.58   259.3  516.43   279.2   504.7   287.2  501.68
   303.1  500.51  321.49497.2233   331.1  495.76     347  490.73     355  490.11
   514.5  490.77  526.46494.9806   558.4  499.79   570.4   503.6   622.2   503.5
  672.46506.6919     698  508.19  714.05 511.899   729.9   515.6   793.8  535.21
   829.4  544.37   880.8  555.23   932.1  570.07   951.9  573.81  1007.2  579.27
#Mann= 7 ,-1 , 0
       0     .12       0  321.49     .04       0     347     .04       0
   514.5     .04       0  526.46     .12       0  672.46    .016       0
  714.05     .12       0
Bank Sta=347,514.5
XS Rating Curve= 0 ,0
Exp/Cntr=0.3,0.1

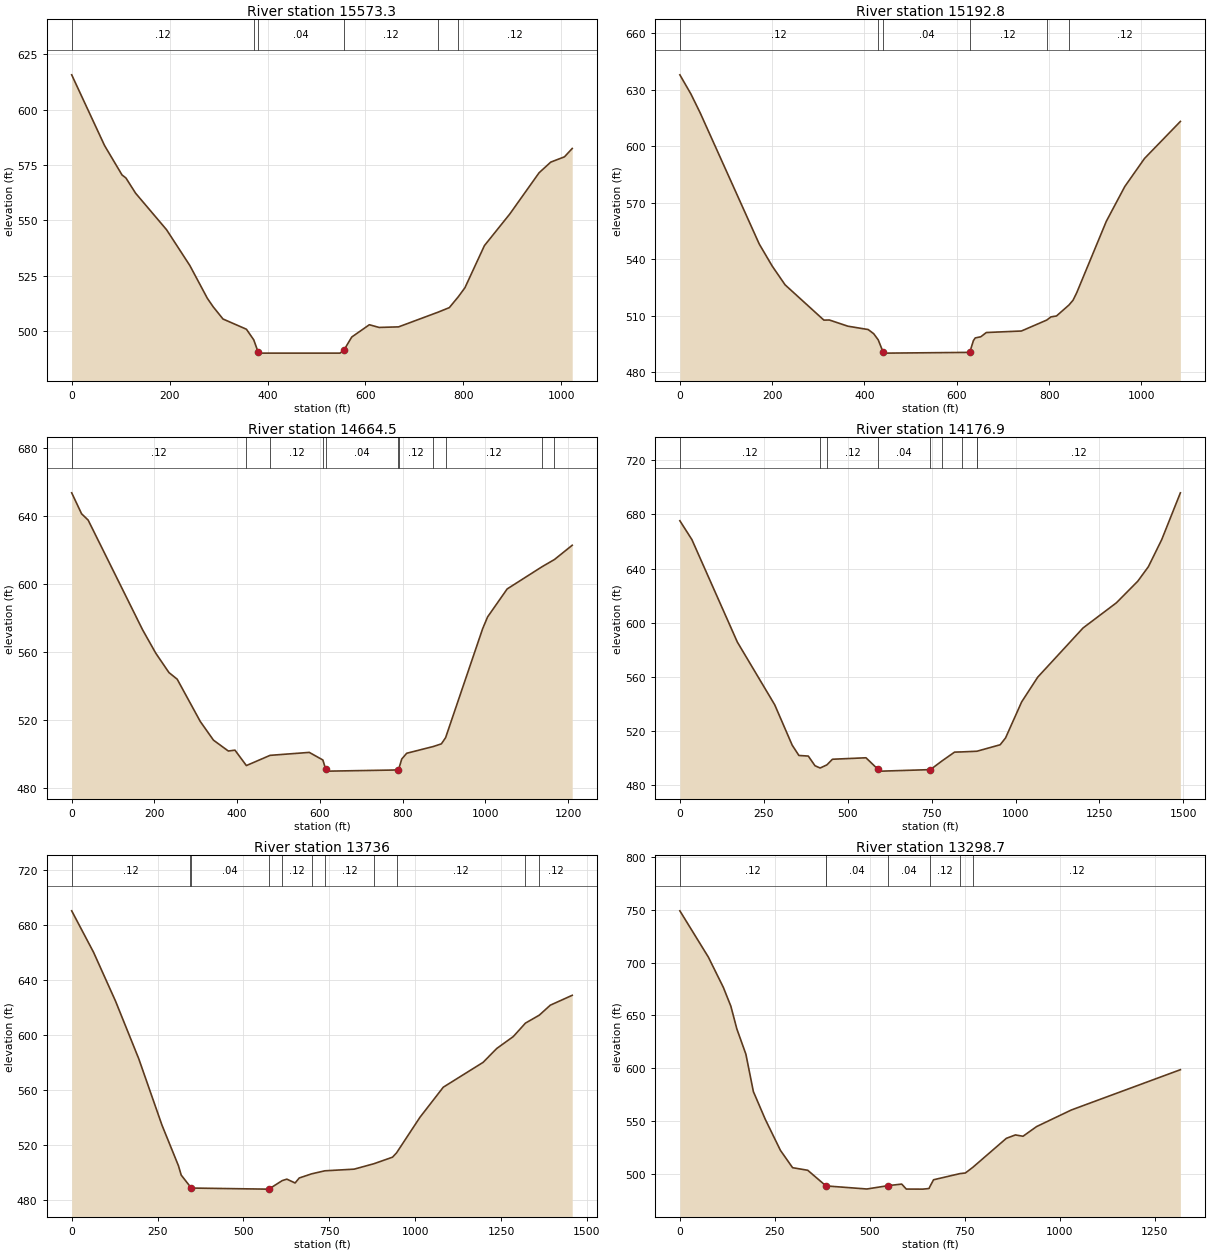
Type RM Length L Ch R = 1 ,15573.3 ,376.2,380.6,384.6
XS GIS Cut Line= 3
     2297216.904      380136.425      2297429.87      380031.669
     2297959.393      379452.007
#Sta/Elev= 30
       0  615.68    67.2  583.75   102.8  570.51   110.8  569.13   130.5  562.28
   193.8  545.78   241.3  529.66   277.2  514.81   289.1  510.99   309.1   505.5
   356.9  500.89  371.86496.1154   380.8  490.61   384.8  490.11   548.2  490.11
   556.2  491.52   572.1  497.38     608  502.92   627.9   501.7   667.8  501.96
  748.78508.6204   771.4  510.64  789.95515.6158   803.2  519.59   843.1  538.63
   894.9  552.89   954.7  571.48   978.6   576.3  1006.5  578.67  1022.4  582.44
#Mann= 6 ,-1 , 0
       0     .12       0  371.86     .04       0   380.8     .04       0
   556.2     .12       0  748.78    .016       0  789.95     .12       0
Bank Sta=380.8,556.2
XS Rating Curve= 0 ,0
Exp/Cntr=0.3,0.1

Type RM Length L Ch R = 1 ,15192.8 ,523.1,528.3,533.8
XS GIS Cut Line= 3
     2297428.724      380443.322     2298202.448      379861.729
     2298313.559      379827.007
#Sta/Elev= 30
       0  637.94      24  627.74      44  617.75     172  548.06     200  536.38
     228  526.38     312  507.65     324   507.7     364  504.42     408  502.64
     420  500.41   429.8 497.127     440  490.86     448  490.11     628  490.51
     636  496.78     640  498.18     652   498.8     664  501.06     740  501.86
  794.85507.6734     804  509.36     816  509.85  843.06515.6838   851.9  518.25
   859.9  522.24   923.9  560.12   963.9  578.58  1006.7  593.52  1084.4  613.18
#Mann= 6 ,-1 , 0
       0     .12       0   429.8     .04       0     440     .04       0
     628     .12       0  794.85    .016       0  843.06     .12       0
Bank Sta=440,628
XS Rating Curve= 0 ,0
Exp/Cntr=0.3,0.1

Type RM Length L Ch R = 1 ,14664.5 ,478,487.6,496.9
XS GIS Cut Line= 4
       2297549.6      380745.455     2297827.448      380674.229
     2298494.115      380386.034     2298636.476      380250.618
#Sta/Elev= 30
       0  653.82    23.9   641.5    39.8  637.77   171.3  573.27   203.2  559.49
     235  548.11     255  544.18   310.8   519.3   342.7  508.32   378.6  501.93
   394.6  502.44  422.17493.3817  479.48499.3891   574.2  501.13  607.01496.6544
   614.1  491.07     622  490.11   789.6   490.8  790.75491.6683   797.6  497.22
   809.6  500.62   874.1504.6002   893.4  506.15  903.63509.7984   993.2  573.93
  1005.1  580.82  1052.4  597.28 1136.25610.2858  1166.7614.5854  1209.6  622.98
#Mann= 11 ,-1 , 0
       0     .12       0  422.17     .04       0  479.48     .12       0
  607.01     .04       0   614.1     .04       0   789.6     .04       0
  790.75     .12       0   874.1    .016       0  903.63     .12       0
 1136.25    .016       0  1166.7     .12       0
Bank Sta=614.1,789.6
XS Rating Curve= 0 ,0
Exp/Cntr=0.3,0.1

Type RM Length L Ch R = 1 ,14176.9 ,436.9,440.9,445.1
XS GIS Cut Line= 4
     2297595.139      381021.314     2297863.898      380964.829
     2298623.446      380977.849       2299072.5      380893.509
#Sta/Elev= 30
       0  675.35    35.8  661.41   171.2  585.61   282.6  539.19   334.6  509.36
   354.6   501.7   382.6  501.25   402.6   494.1  417.87492.4195  437.98494.7139
   454.6   498.9   554.5  499.98   590.5   491.4   602.5  490.11   746.4  491.22
  781.71 497.783   818.4  504.18  840.43504.3304  884.61 504.825   885.9504.8863
   954.3  509.61   970.3  514.67  1018.3  541.33  1066.1  559.61  1201.2  596.01
  1300.5  614.62  1364.1  630.56  1395.8  641.32  1435.6  661.38  1491.2  695.99
#Mann= 9 ,-1 , 0
       0     .12       0  417.87     .04       0  437.98     .12       0
   590.5     .04       0   746.4     .04       0  781.71     .12       0
  840.43    .016       0  884.61     .06       0   885.9     .12       0
Bank Sta=590.5,746.4
XS Rating Curve= 0 ,0
Exp/Cntr=0.3,0.1

Type RM Length L Ch R = 1 ,13736   ,439.8,437.3,434.8
XS GIS Cut Line= 4
     2297599.937      381347.569     2297846.536      381333.752
     2298588.724      381472.641     2299018.117      381623.788
#Sta/Elev= 30
       0  690.36    63.7  660.17   127.5  624.74   195.2  582.75     263   534.3
   310.9   504.8   318.9  498.02  343.67490.1119   346.9  488.61   566.6  487.82
   574.6  487.93   612.9 494.008   626.5  495.08   650.5   492.3   662.5  495.93
  698.86498.9628  737.12501.1528   822.3  502.35  880.09506.3154   934.1  511.07
  945.89514.2323    1014  540.11  1081.9     562  1197.7  580.06  1237.6  590.19
  1285.6  598.83 1321.18608.6472 1361.44614.4271  1393.4  621.68  1457.3  628.88
#Mann= 11 ,-1 , 0
       0     .12       0  343.67     .04       0   346.9     .04       0
   574.6     .04       0   612.9     .12       0  698.86    .016       0
  737.12     .12       0  880.09    .016       0  945.89     .12       0
 1321.18    .016       0 1361.44     .12       0
Bank Sta=346.9,574.6
XS Rating Curve= 0 ,0
Exp/Cntr=0.3,0.1

Type RM Length L Ch R = 1 ,13298.7 ,441.4,444.4,447.3
XS GIS Cut Line= 4
     2297556.615      381733.257     2297803.134      381789.481
     2298479.794      381838.701     2298823.976      382014.507
#Sta/Elev= 30
       0  748.85    75.1   705.1   114.6  676.44   134.3  658.72   150.1  637.21
   173.8  613.46   193.6  578.04   225.2  551.65   264.8  522.56   296.8  506.19
   336.7  503.75  383.94489.2177   384.6  488.99   492.3  486.06   548.2  489.22
   584.1  490.71   596.1     486     640  485.94   655.9  486.52  659.48489.1334
   667.9  494.78  737.43 500.597   751.7  501.19  771.75506.6627   859.5  533.91
   883.4  537.14   903.4  535.89   939.3  545.05  1030.9  560.74  1317.8  598.76
#Mann= 7 ,-1 , 0
       0     .12       0  383.94     .04       0   384.6     .04       0
   548.2     .04       0  659.48     .12       0  737.43    .016       0
  771.75     .12       0
Bank Sta=384.6,548.2
XS Rating Curve= 0 ,0
Exp/Cntr=0.3,0.1

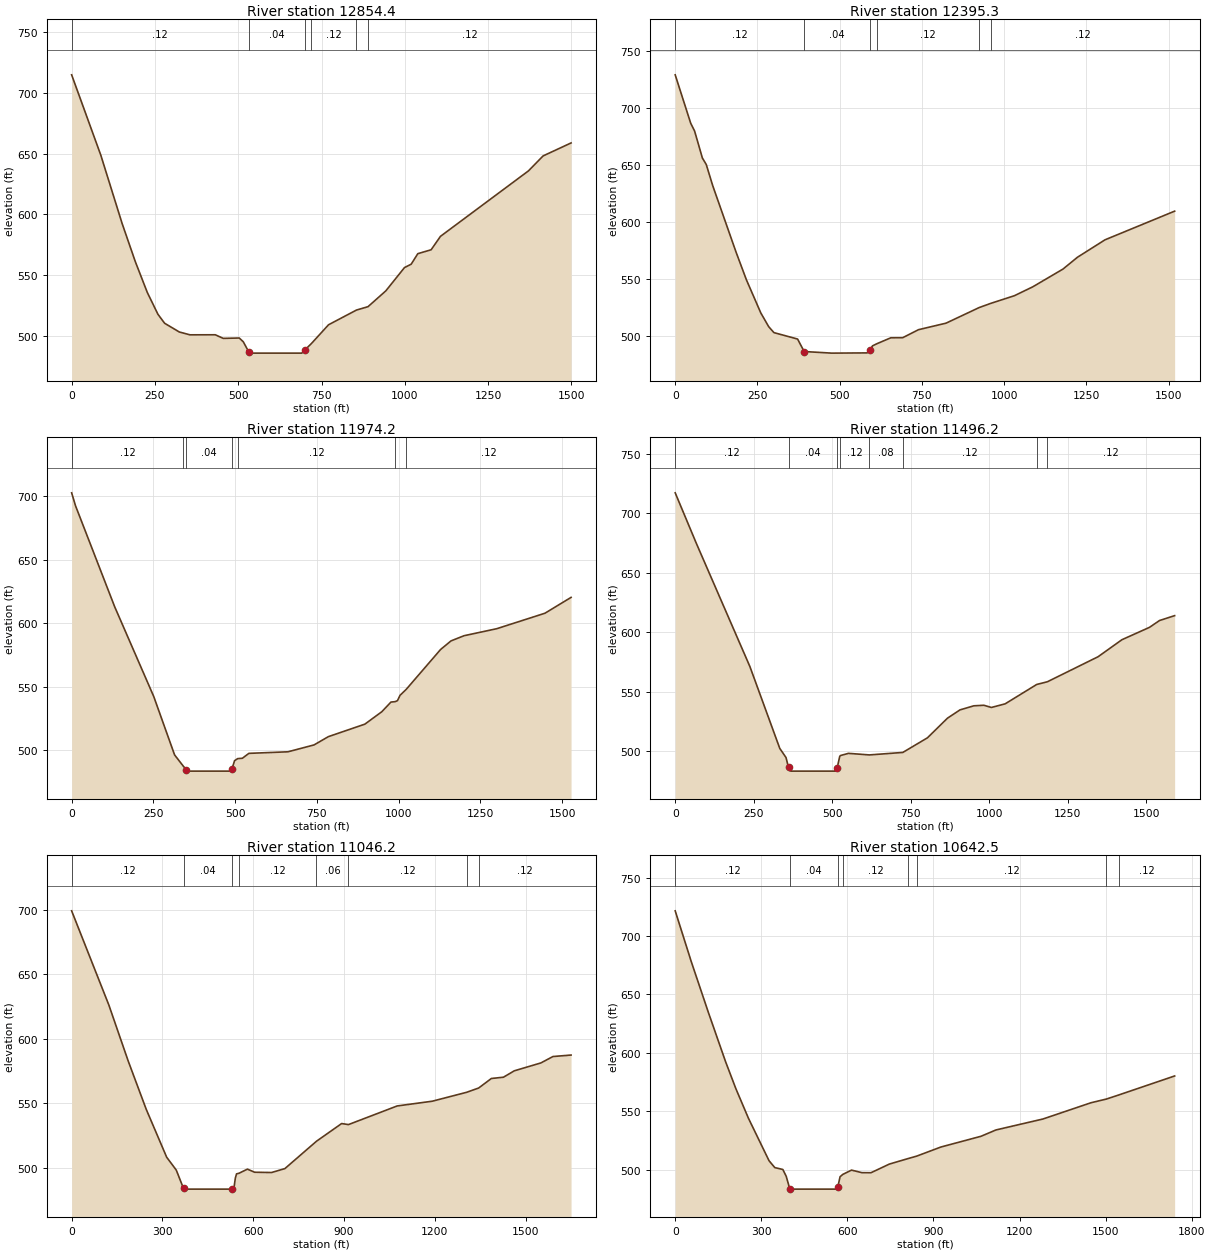
Type RM Length L Ch R = 1 ,12854.4 ,455,459,463.1
XS GIS Cut Line= 3
     2297457.342      382114.759     2297677.266      382171.426
     2298922.681      382429.908
#Sta/Elev= 30
       0  715.05    87.7   648.7   151.4  592.58   191.2  560.98   227.1  535.64
   259.1  517.61   279.1  510.23   323.1  503.04   355.1  500.69   431.1  500.73
   455.1  497.76   503.1  498.07   515.1  494.99   531.1   486.9   539.1   485.6
   691.1   485.6   699.1  487.96  719.51 493.442   771.1  508.97     855521.1145
  889.63523.9063   943.1  536.94   999.1  556.14  1019.1   558.9  1039.1  567.59
  1079.1  570.83  1107.1  581.89  1371.1  635.83  1415.1  648.18  1499.1   658.9
#Mann= 6 ,-1 , 0
       0     .12       0   531.1     .04       0   699.1     .04       0
  719.51     .12       0     855    .016       0  889.63     .12       0
Bank Sta=531.1,699.1
XS Rating Curve= 0 ,0
Exp/Cntr=0.3,0.1

Type RM Length L Ch R = 1 ,12395.3 ,422.2,421.1,420.1
XS GIS Cut Line= 3
     2297353.006      382465.832     2297568.759      382540.349
     2298762.678      383028.299
#Sta/Elev= 30
       0  729.46    47.2  686.87      59  680.05    82.6   656.4    94.4  650.69
   114.1  632.06     185  573.69   216.4  549.42   260.2  520.28   284.2  508.23
   300.1  503.01     372  497.35     392   486.4   475.8  484.99   583.6  485.19
   591.6  487.46   599.6  491.34  613.05493.2548   655.5  498.48   691.5  498.54
   739.4  505.57   823.2  511.31  923.76524.9949  958.92 528.676  1030.9  535.42
  1086.8  543.23  1178.6  558.82  1222.6   569.2  1306.4  584.53    1518   609.7
#Mann= 6 ,-1 , 0
       0     .12       0     392     .04       0   591.6     .04       0
  613.05     .12       0  923.76    .016       0  958.92     .12       0
Bank Sta=392,591.6
XS Rating Curve= 0 ,0
Exp/Cntr=0.3,0.1

Type RM Length L Ch R = 1 ,11974.2 ,481.2,478,475
XS GIS Cut Line= 3
     2297230.715      382874.744     2298137.335      383191.391
     2298695.251      383290.911
#Sta/Elev= 30
       0  702.76      12  692.46   131.5  612.97     251  542.14   314.8  496.04
  341.95 487.015   350.7  484.53   358.6  483.26   482.2  483.26   490.1  484.74
   498.1  491.47  507.56493.1148     522   493.4   541.9  497.27   661.5  498.51
   741.2  503.93     785  510.46   896.6  520.32   948.4  530.12   976.3  537.72
  989.35 538.072   996.2  538.84  1004.2  543.11 1022.67547.6616    1128  579.18
  1159.9  585.97  1199.8  590.06  1299.6  595.58  1447.2   607.8    1527   620.3
#Mann= 7 ,-1 , 0
       0     .12       0  341.95     .04       0   350.7     .04       0
   490.1     .04       0  507.56     .12       0  989.35    .016       0
 1022.67     .12       0
Bank Sta=350.7,490.1
XS Rating Curve= 0 ,0
Exp/Cntr=0.3,0.1

Type RM Length L Ch R = 1 ,11496.2 ,450.4,450,447.8
XS GIS Cut Line= 4
     2297076.761      383389.526     2297512.488      383475.794
     2297973.701      383571.424      2298644.84      383493.259
#Sta/Elev= 30
       0  717.36    67.4  674.82     238  571.19   333.1  502.39     353  494.69
   360.9  486.37   364.9  483.62   368.8  483.26     508  483.26     512  483.45
     516  486.05     524  495.53  526.16496.3508     552  498.21   618.6 496.885
  725.11498.9854   803.4  511.26   867.3   527.8   907.2  534.78   951.2   538.2
   983.2  538.67  1007.2   536.8  1051.1  539.87 1151.64556.1672 1185.57558.4294
    1347  579.48    1423   593.8  1510.9  604.22  1542.9  609.96  1590.9  614.05
#Mann= 8 ,-1 , 0
       0     .12       0   360.9     .04       0     516     .04       0
  526.16     .12       0   618.6     .08       0  725.11     .12       0
 1151.64    .016       0 1185.57     .12       0
Bank Sta=360.9,516
XS Rating Curve= 0 ,0
Exp/Cntr=0.3,0.1

Type RM Length L Ch R = 1 ,11046.2 ,407.8,403.7,401.2
XS GIS Cut Line= 3
     2296995.731      383839.905     2297429.734      383918.103
     2298631.544      384046.909
#Sta/Elev= 30
       0  699.45   123.2  626.11   186.7  582.88   246.3  545.32   313.9  508.06
   345.6  498.06   369.5  483.84   377.4  483.26   528.8  483.26   536.7  485.01
   540.7  491.78   544.7   495.1  552.91495.5984   580.6  498.78   604.5  496.38
   660.4  496.16   704.3  499.19  808.75520.4568   891.8   534.2  914.49533.4061
  1075.3  547.87  1190.9  551.54 1304.66558.4733 1344.49561.8121  1386.4   569.2
  1426.3   570.2  1462.2  575.17    1550  581.29  1589.8  586.26  1649.7  587.41
#Mann= 8 ,-1 , 0
       0     .12       0   369.5     .04       0   528.8     .04       0
  552.91     .12       0  808.75     .06       0  914.49     .12       0
 1304.66    .016       0 1344.49     .12       0
Bank Sta=369.5,528.8
XS Rating Curve= 0 ,0
Exp/Cntr=0.3,0.1

Type RM Length L Ch R = 1 ,10642.5 ,441.3,437.4,433.6
XS GIS Cut Line= 3
     2296920.138       384308.79     2297191.154      384319.863
      2298660.57       384316.43
#Sta/Elev= 30
       0  721.67    55.8   678.3   115.7  634.58   175.5  592.49   211.4  569.35
   255.3  543.96   327.1  507.58   347.1  501.71   375.1   500.1     387  494.19
     399  483.74     403  483.26   562.7  483.26   566.7  485.08   574.7  493.91
  584.35495.8987   614.6  499.55   650.6  497.37   682.5  497.32   746.4  504.72
  812.47509.4939  841.99511.5537   926.1  519.33  1065.8  528.53  1117.8  533.94
  1281.5  543.32  1449.2  557.26 1502.53560.3959 1545.09563.8468  1740.7   580.2
#Mann= 8 ,-1 , 0
       0     .12       0     399     .04       0   566.7     .04       0
  584.35     .12       0  812.47     .06       0  841.99     .12       0
 1502.53    .016       0 1545.09     .12       0
Bank Sta=399,566.7
XS Rating Curve= 0 ,0
Exp/Cntr=0.3,0.1

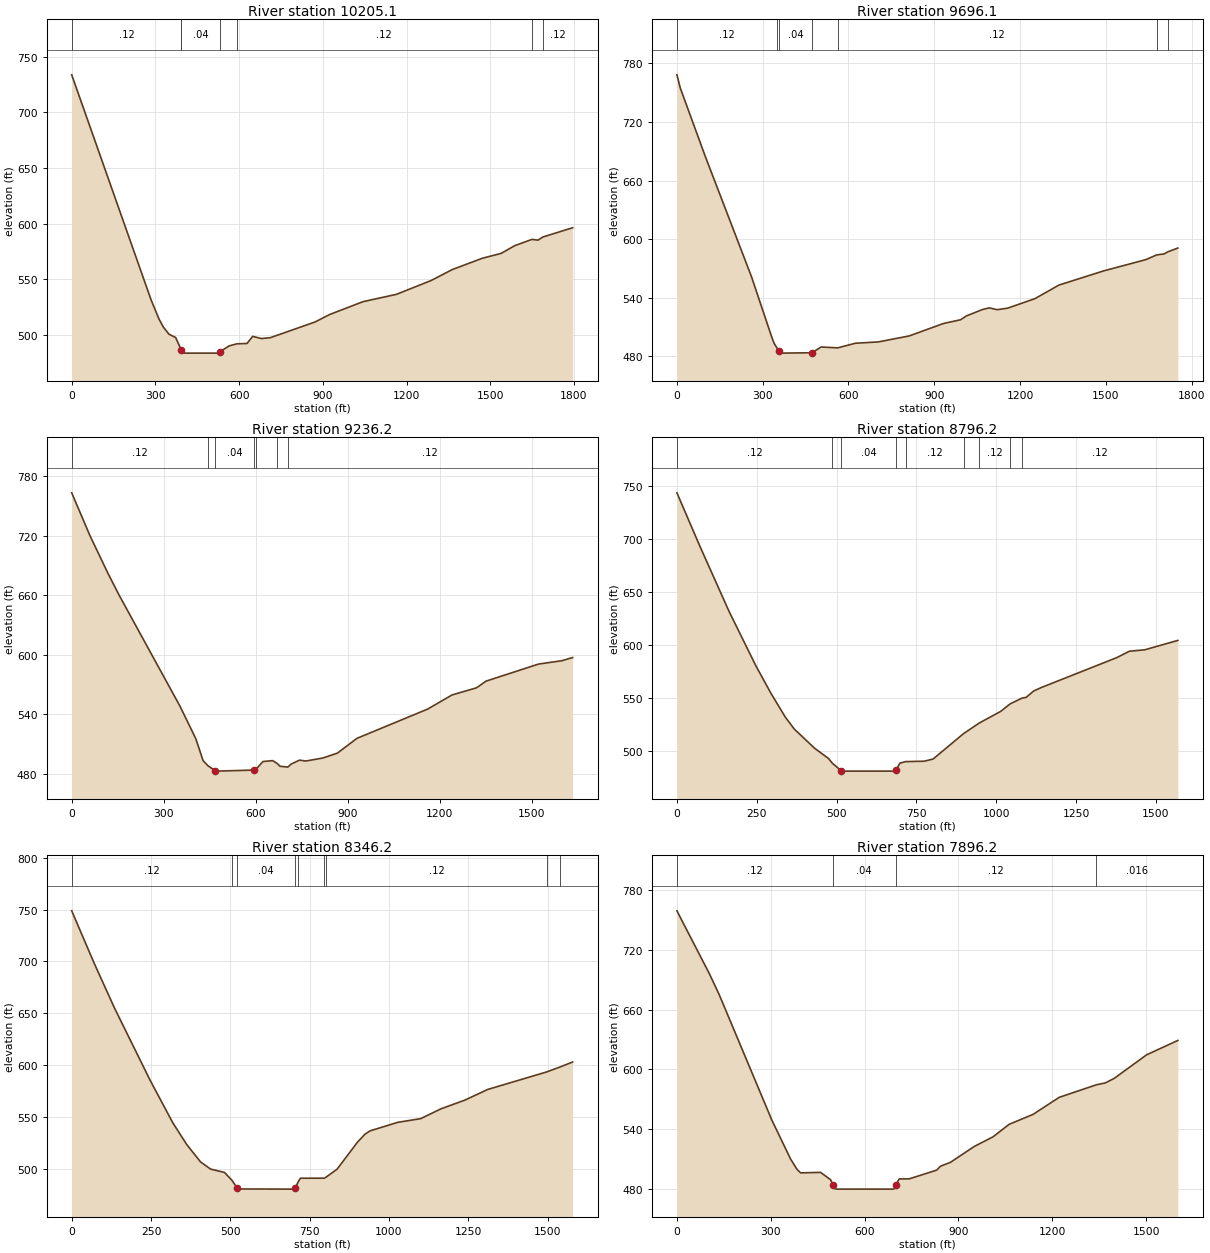
Type RM Length L Ch R = 1 ,10205.1 ,513.9,508.9,504
XS GIS Cut Line= 3
     2296911.462      384811.979     2297191.154      384788.613
     2298683.362      384528.069
#Sta/Elev= 30
       0   733.9   284.7  531.08   312.6  514.11   328.6  506.65   348.6  500.32
   372.6   497.3  392.21486.3247   392.6  486.08   400.6  483.26   524.5  483.26
   532.5  484.71   564.4  489.78  591.56491.6296   628.4  491.97   648.4  498.35
   680.4  496.39   712.3  497.21   872.2  511.32   924.2  518.01    1044   529.6
    1164  536.22  1287.9  548.62  1363.8  558.49  1471.7  568.69  1539.6  573.12
  1587.6  580.04 1649.28585.6628  1671.6  585.02 1688.51587.8333  1795.4  596.19
#Mann= 7 ,-1 , 0
       0     .12       0  392.21     .04       0   392.6     .04       0
   532.5     .04       0  591.56     .12       0 1649.28    .016       0
 1688.51     .12       0
Bank Sta=392.6,532.5
XS Rating Curve= 0 ,0
Exp/Cntr=0.3,0.1

Type RM Length L Ch R = 1 ,9696.1  ,463.6,459.9,456.2
XS GIS Cut Line= 3
     2297069.354      385383.466     2297334.384      385305.106
     2298698.232      384742.122
#Sta/Elev= 30
       0   768.3    11.8  754.75    98.7  685.12   260.6   561.7   332.4  499.03
   340.4  493.02  349.36488.8436   356.3  485.15   364.3  483.26   472.3  483.65
   504.3  489.54  562.35488.6539   624.2   493.4   704.2  494.74   812.2  500.86
   932.1  513.59   992.1  517.46  1012.1  521.32  1068.1  527.89  1092.1  529.61
  1120.1  527.76  1156.1  529.27    1252  539.06    1336  552.97  1491.9  567.45
  1639.9  579.02 1677.48583.8433  1703.9  584.87 1716.12586.9337  1751.8  590.91
#Mann= 7 ,-1 , 0
       0     .12       0  349.36     .04       0   356.3     .04       0
   472.3     .04       0  562.35     .12       0 1677.48    .016       0
 1716.12     .12       0
Bank Sta=356.3,472.3
XS Rating Curve= 0 ,0
Exp/Cntr=0.3,0.1

Type RM Length L Ch R = 1 ,9236.2  ,444.9,440,436.4
XS GIS Cut Line= 4
     2297329.149      385918.116     2297625.182       385678.37
     2298185.078      385326.808     2298746.137      385137.311
#Sta/Elev= 30
       0  763.05    59.5  719.96     119   681.5   154.8  659.94   353.2  548.25
   404.8  515.52   428.7  493.39  444.16488.3556   468.6  483.05   472.5  482.85
     596  483.93  600.53484.4308   623.9  492.51   655.7  493.43  670.67490.4944
   679.6  487.76  705.17 486.933   715.5   489.9   743.4  493.93   763.3  493.01
     819  496.03   866.8  500.98   930.5  515.85  1161.3  545.33  1240.8  559.55
  1320.3   566.7  1352.1   573.5    1523  590.65  1598.5  593.98  1634.2   597.2
#Mann= 7 ,-1 , 0
       0     .12       0  444.16     .04       0   468.6     .04       0
     596     .04       0  600.53     .12       0  670.67     .04       0
  705.17     .12       0
Bank Sta=468.6,596
XS Rating Curve= 0 ,0
Exp/Cntr=0.3,0.1

Type RM Length L Ch R = 1 ,8796.2  ,448.9,450,448.7
XS GIS Cut Line= 3
     2297649.075      386309.749     2298061.251      385909.349
     2298809.796      385255.058
#Sta/Elev= 30
       0  743.22    71.8  692.96   163.6  631.22   247.4  580.04   295.3  553.76
   339.2  531.86   367.1  520.61     431  502.43   474.9  492.68  486.33488.3802
   514.8  481.05   518.8   480.8   678.4   480.8   686.4  482.03   698.4  488.32
   715.9  489.77   774.3  490.15   802.2  492.19  897.75 516.187  947.41526.2642
  1013.8  537.09 1043.82 544.263 1081.52549.7309  1093.7  550.33  1117.6  556.43
  1141.6  559.68  1377.2  587.79  1417.1  593.86    1465  595.19  1568.8  604.05
#Mann= 9 ,-1 , 0
       0     .12       0  486.33     .04       0   514.8     .04       0
   686.4     .04       0   715.9     .12       0  897.75    .016       0
  947.41     .12       0 1043.82     .08       0 1081.52     .12       0
Bank Sta=514.8,686.4
XS Rating Curve= 0 ,0
Exp/Cntr=0.3,0.1

Type RM Length L Ch R = 1 ,8346.2  ,446.1,450,453.4
XS GIS Cut Line= 3
     2297917.578      386633.117     2298375.413      386231.532
     2299069.266      385553.539
#Sta/Elev= 30
       0  748.84    71.6  697.71   135.3  654.74   246.8  585.52   318.4  544.39
   362.2  523.42     406  506.53   437.8  499.54   481.6  496.35   504.7 488.864
   521.4   481.5   529.4  480.36   696.8  480.21   704.8  481.26  713.39486.9875
   720.8  490.72  796.61490.7821  802.79491.9814   836.6  499.48   900.4  525.37
   924.4  533.22   940.4  536.44  1028.2  544.71    1100  548.22  1163.9   557.7
  1239.8  566.18  1311.6  576.44 1496.87593.2949 1538.73598.0431  1579.1   602.9
#Mann= 9 ,-1 , 0
       0     .12       0   504.7     .04       0   521.4     .04       0
   704.8     .04       0  713.39     .12       0  796.61    .016       0
  802.79     .12       0 1496.87    .016       0 1538.73     .12       0
Bank Sta=521.4,704.8
XS Rating Curve= 0 ,0
Exp/Cntr=0.3,0.1

Type RM Length L Ch R = 1 ,7896.2  ,418.4,418.1,419.7
XS GIS Cut Line= 3
     2298142.372      386894.364     2298667.173      386573.556
     2299469.229       385998.81
#Sta/Elev= 30
       0  759.08   103.8     696   135.8  674.61   303.6  549.17   363.5  510.15
   383.4  500.09   395.4  496.27   459.3   496.8   491.3  489.42   499.3  484.37
   503.2  480.74   511.2  479.98     691  479.99     695  480.34     699  484.11
     711  490.24   742.9  490.29   830.8  499.06   842.8  502.95   874.8  506.89
   950.6  522.74  1010.6  532.39  1062.5     545  1138.4  554.87  1222.3     572
  1340.9 584.586  1370.1  586.52  1398.1  591.02  1501.9  614.68  1601.8  629.09
#Mann= 4 ,-1 , 0
       0     .12       0   499.3     .04       0     699     .12       0
  1340.9    .016       0
Bank Sta=499.3,699
XS Rating Curve= 0 ,0
Exp/Cntr=0.3,0.1

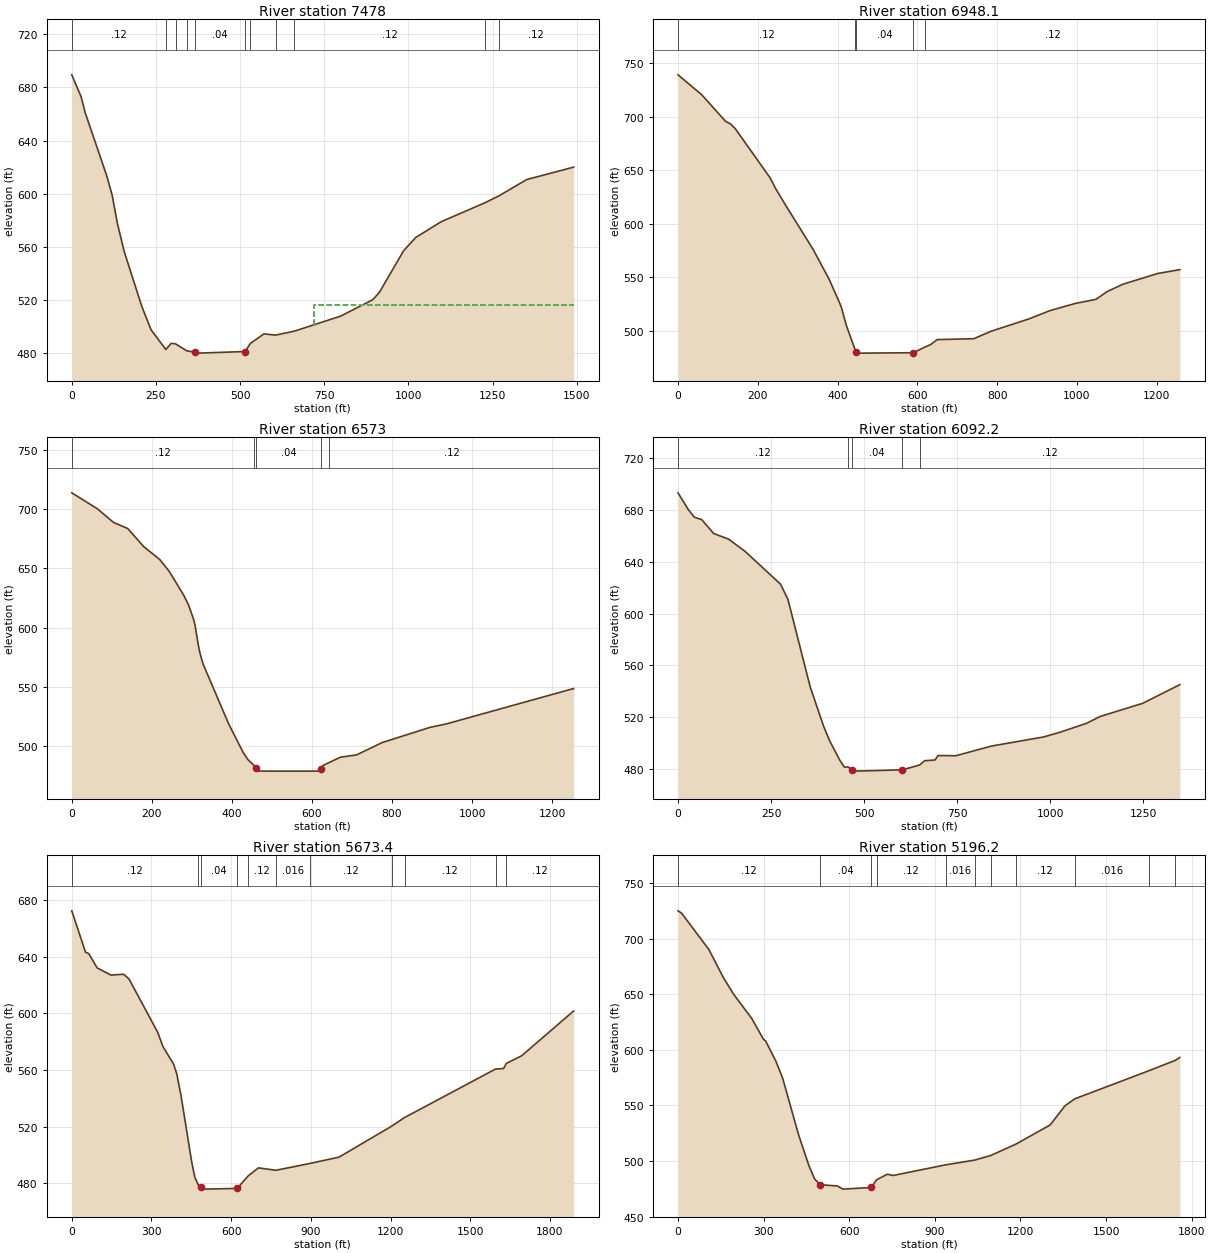
Type RM Length L Ch R = 1 ,7478    ,527.3,530,532.6
XS GIS Cut Line= 3
     2298487.171      387163.812     2299247.587      386708.951
     2299647.256      386255.579
#Sta/Elev= 30
       0  689.52    27.9  672.96    39.9  661.04   103.8  613.57   119.7  599.18
   135.7   577.5   155.7  556.56   207.6  515.47   235.5  497.59  279.36482.7216
   295.4  487.39  308.27486.9648  341.96481.6517   367.2  480.75   375.2  479.98
   514.9  481.18  530.58487.3326   570.8  494.46  605.31493.5425  661.39496.5423
   798.3   507.8     894  520.21   913.9  525.83   985.5  557.03  1021.3     567
  1096.8  578.88 1227.18593.2044 1268.39598.3571  1351.3  610.67  1490.5  620.03
#Mann= 11 ,-1 , 0
       0     .12       0  279.36     .04       0  308.27     .12       0
  341.96     .08       0   367.2     .04       0   514.9     .04       0
  530.58     .12       0  605.31     .08       0  661.39     .12       0
 1227.18    .016       0 1268.39     .12       0
#XS Ineff= 2 , 0
                          720.45          515.92
Permanent Ineff=
       F       F
Bank Sta=367.2,514.9
XS Rating Curve= 0 ,0
Exp/Cntr=0.3,0.1

Type RM Length L Ch R = 1 ,6948.1  ,373.8,375.1,376.1
XS GIS Cut Line= 4
     2298544.688       387625.32     2298893.411      387500.419
     2299427.266      387248.683     2299719.809      387195.062
#Sta/Elev= 30
       0  739.33    59.7  720.62   119.5  695.76   131.4  693.49   143.4  689.08
     231     643     243  634.16   270.8  616.81   338.6   576.2   378.4  548.58
   406.3  525.15   410.3  520.95   422.3  504.75  444.15482.1026   446.2  480.56
   454.2  479.16   589.8  479.53  620.34485.0416   633.6  487.23   649.6   491.8
   741.3  492.64   785.2  499.66   880.9  511.29   932.7  518.95   996.3  525.63
  1047.9  529.45  1075.6  536.67  1115.3  543.56  1202.6  553.62  1258.1  557.23
#Mann= 5 ,-1 , 0
       0     .12       0  444.15     .04       0   446.2     .04       0
   589.8     .04       0  620.34     .12       0
Bank Sta=446.2,589.8
XS Rating Curve= 0 ,0
Exp/Cntr=0.3,0.1

Type RM Length L Ch R = 1 ,6573    ,475.6,480.8,485.9
XS GIS Cut Line= 3
     2298700.947      387974.821     2299584.393      387611.729
     2299827.448      387438.118
#Sta/Elev= 30
       0   714.1    63.9  700.62   103.9  689.14   139.9  683.85   179.8  668.53
   219.8   657.6   243.8  647.42   279.8  627.33   291.7  619.12   303.7  607.66
   307.7  602.59   315.7     586   319.7  579.14   327.7  569.37   391.6  518.68
   427.6  494.53   439.6  488.28  455.73482.9675   459.6  480.81   467.6  478.34
   615.4  478.34   623.4  480.07   627.4  483.05   643.1 485.643   671.4  490.15
   711.4  492.08   775.3   502.5   895.2  515.44   935.2  518.28  1253.8  548.31
#Mann= 5 ,-1 , 0
       0     .12       0  455.73     .04       0   459.6     .04       0
   623.4     .04       0   643.1     .12       0
Bank Sta=459.6,623.4
XS Rating Curve= 0 ,0
Exp/Cntr=0.3,0.1

Type RM Length L Ch R = 1 ,6092.2  ,418.3,418.8,419.3
XS GIS Cut Line= 3
     2298772.995      388325.483     2299817.032      388156.868
     2300073.976      388021.451
#Sta/Elev= 30
       0  693.23    27.9  680.19    43.9  674.41    63.8  672.53    95.8  661.83
   135.7  657.51   179.6  648.16   275.4  622.71   295.3  610.96   355.2  543.26
   391.1  512.99   407.1   501.9     435  486.57     447   481.4  456.98481.5925
   466.9  479.26   474.9  478.34   602.6  479.33  649.43 483.122   662.5  486.38
   690.4  486.96   698.4  490.38   746.3  490.22   842.1   497.7   981.7   504.7
  1025.6  508.31  1097.4  515.27  1133.2  520.47  1248.5  530.73    1348  545.13
#Mann= 5 ,-1 , 0
       0     .12       0  456.98     .04       0   466.9     .04       0
   602.6     .04       0  649.43     .12       0
Bank Sta=466.9,602.6
XS Rating Curve= 0 ,0
Exp/Cntr=0.3,0.1

Type RM Length L Ch R = 1 ,5673.4  ,475.7,477.3,479.3
XS GIS Cut Line= 3
     2298817.034      388728.417     2299366.848      388653.024
     2300688.252      388467.686
#Sta/Elev= 30
       0  672.54    51.9  643.27    63.9  642.37    95.8  632.16   147.7  627.13
   195.6  627.73   215.6  624.36   323.4  586.75   343.4  576.56   383.3  564.25
   395.3  557.35   411.2  542.09   451.2  495.51   463.1  484.38  476.67478.6999
   487.1  477.13   499.1  475.88   622.9  476.39  664.14 485.231   702.8   490.9
  768.58 489.201  898.38 494.091  1006.4   498.5 1204.24520.3687 1252.95526.4704
 1595.28560.7291  1625.6  561.11 1635.96564.7277  1693.5  570.09  1889.3  601.78
#Mann= 11 ,-1 , 0
       0     .12       0  476.67     .04       0   487.1     .04       0
   622.9     .04       0  664.14     .12       0  768.58    .016       0
  898.38     .12       0 1204.24    .016       0 1252.95     .12       0
 1595.28    .016       0 1635.96     .12       0
Bank Sta=487.1,622.9
XS Rating Curve= 0 ,0
Exp/Cntr=0.3,0.1

Type RM Length L Ch R = 1 ,5196.2  ,446.7,450,452.9
XS GIS Cut Line= 3
     2298850.176      389163.401     2299443.004      389123.381
     2300606.215      389066.039
#Sta/Elev= 30
       0  725.03      12  723.07   107.7  690.45   159.5  664.77   195.4   649.8
   259.2  627.95   299.1  609.61   307.1  607.97     343  589.75   366.9  574.37
   422.7  523.42   458.6  495.94   478.5  483.87   498.5   478.6   558.3  477.51
   578.2  474.65   677.9  476.17  695.94483.0857   733.8  488.04   753.7  486.93
  937.79496.4936 1039.58500.7608 1095.62504.8674  1183.3 515.023  1304.1  532.35
    1356  549.57 1389.97555.8191 1650.54581.2114 1742.35590.4554  1758.8  593.07
#Mann= 11 ,-1 , 0
       0     .12       0   498.5     .04       0   677.9     .04       0
  695.94     .12       0  937.79    .016       0 1039.58     .12       0
 1095.62    .016       0  1183.3     .12       0 1389.97    .016       0
 1650.54     .12       0 1742.35    .016       0
Bank Sta=498.5,677.9
XS Rating Curve= 0 ,0
Exp/Cntr=0.3,0.1