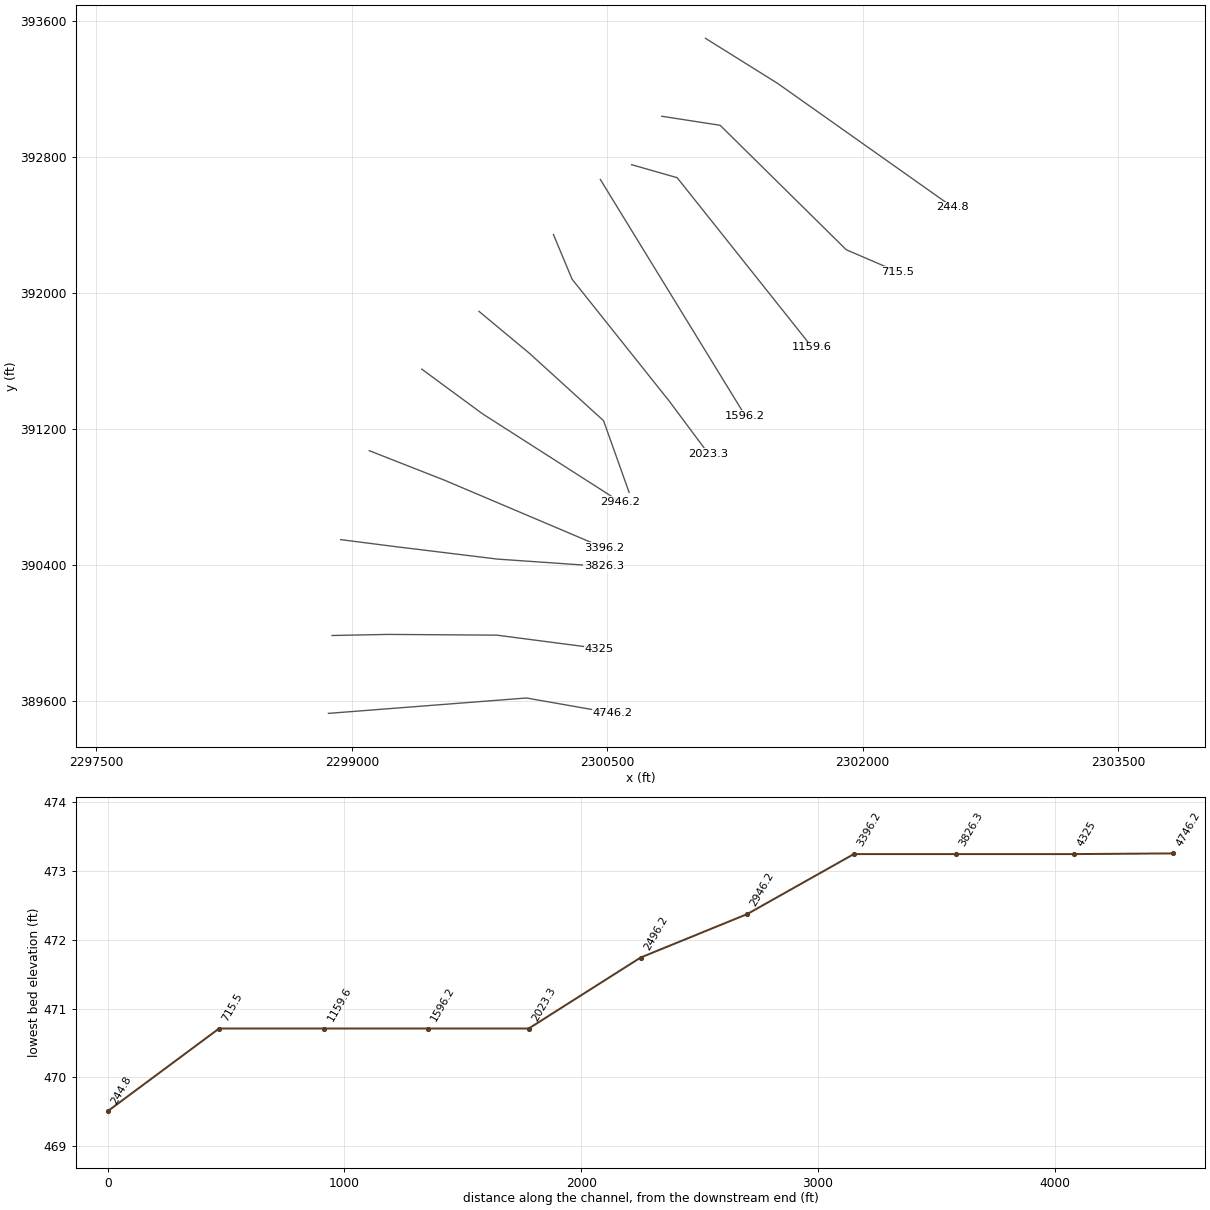
HEC-RAS study CACAPONRIV.prj: CACAPONRIV

--- CACAPONRIV.g01 (geometry) --- (continued)

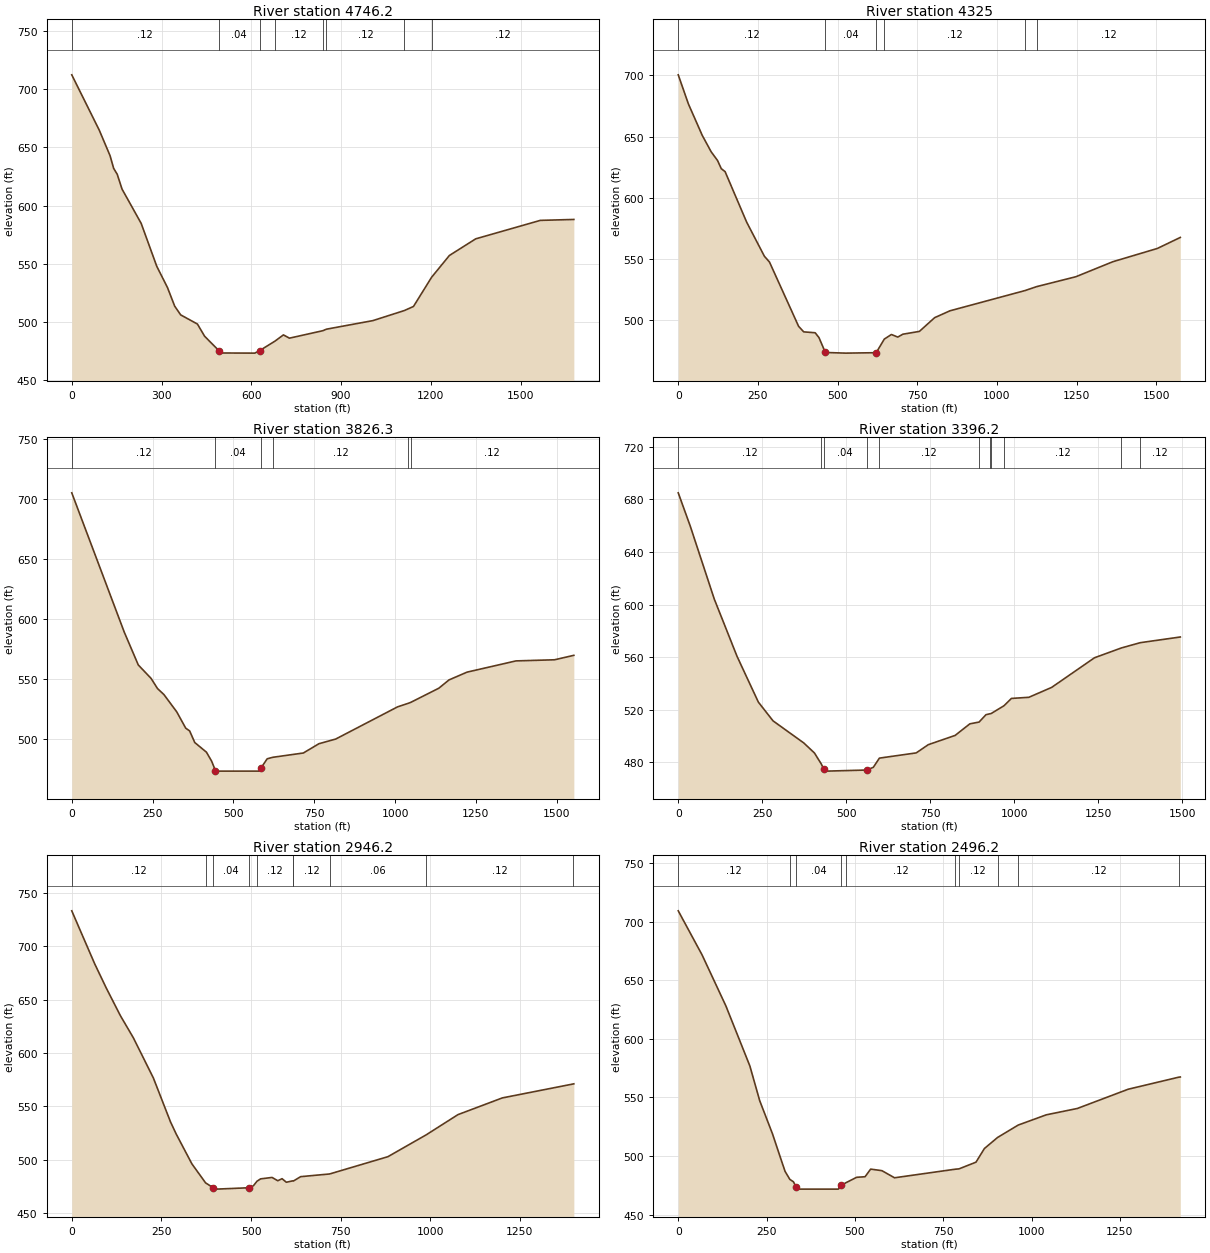
Type RM Length L Ch R = 1 ,4746.2  ,423,421.1,419.2
XS GIS Cut Line= 4
     2298863.096      389528.366     2299429.348      389572.408
     2300025.736      389618.793     2300529.955      389530.113
#Sta/Elev= 30
       0  712.44      92  664.82     128  642.95     140  632.07     152  626.93
     168  614.24     232  584.75     284  547.93     320  529.56     344  513.63
     364  506.13     420  498.24     444  487.76     492  475.33     500  473.37
   611.8  473.25   627.8  475.38  678.88483.5172   707.5  488.92   727.5  486.11
  839.49492.5449  851.04493.8229  1006.6   501.2 1111.82509.8588  1142.2  513.38
 1202.76 538.478  1262.1  557.17  1350.1  571.47  1566.1  587.34  1678.1  588.14
#Mann= 8 ,-1 , 0
       0     .12       0     492     .04       0   627.8     .04       0
  678.88     .12       0  839.49    .016       0  851.04     .12       0
 1111.82    .016       0 1202.76     .12       0
Bank Sta=492,627.8
XS Rating Curve= 0 ,0
Exp/Cntr=0.3,0.1

Type RM Length L Ch R = 1 ,4325    ,501.4,498.8,496.2
XS GIS Cut Line= 4
     2298883.908      389986.213     2299213.724      389992.606
     2299851.745      389988.266     2300453.789      389909.738
#Sta/Elev= 30
       0  700.33    31.8  676.64    75.5  650.84   103.3  637.54   123.2  630.46
   135.1  623.74     147  621.34   214.6  580.16   270.3   552.3   286.2   547.6
   377.7  495.08   393.7  490.59   429.6  489.86   441.5  485.92   461.5  473.77
   525.3  473.24     621  473.59  646.55484.7125   668.8  488.44   688.8  486.34
   704.7  488.68   756.6  490.97   804.4  502.18   852.3  507.76 1087.41524.2505
 1124.54527.5072  1247.5  535.58  1363.4  547.82  1503.2  558.66  1575.1  567.65
#Mann= 6 ,-1 , 0
       0     .12       0   461.5     .04       0     621     .04       0
  646.55     .12       0 1087.41    .016       0 1124.54     .12       0
Bank Sta=461.5,621
XS Rating Curve= 0 ,0
Exp/Cntr=0.3,0.1

Type RM Length L Ch R = 1 ,3826.3  ,435.8,430.1,423.8
XS GIS Cut Line= 4
     2298934.757      390549.837     2299252.786      390509.099
     2299856.085      390435.315     2300479.349      390392.082
#Sta/Elev= 30
       0  705.49   162.3  589.31   205.8  561.83   245.4  550.62   265.2  542.17
     285  537.17   324.6  522.77   352.6  509.07   364.6  506.82   380.6  497.07
   416.6  489.06   432.6  481.62   444.6  473.54   452.6  473.24   580.5  473.26
   584.5  475.48   604.5  483.52  621.47484.7649   716.5  488.37   764.5   496.1
   816.5  500.01    1008  526.89 1041.15529.8481 1048.66530.6232  1135.4  542.42
  1167.2  549.38  1222.9  555.86  1374.1  565.22  1493.5  566.16  1553.2  569.88
#Mann= 6 ,-1 , 0
       0     .12       0   444.6     .04       0   584.5     .04       0
  621.47     .12       0 1041.15    .016       0 1048.66     .12       0
Bank Sta=444.6,584.5
XS Rating Curve= 0 ,0
Exp/Cntr=0.3,0.1

Type RM Length L Ch R = 1 ,3396.2  ,455.9,450,446.2
XS GIS Cut Line= 3
     2299102.746      391072.816     2299550.332      390896.799
     2300483.177      390500.665
#Sta/Elev= 30
       0  684.97    35.8  659.64   107.3  604.14   174.9  560.65   238.5  525.74
   282.2  511.48   373.6  494.69   405.4  487.05  425.97478.6067   433.2  474.73
   441.2  473.24   560.8  474.07   580.7  476.15  598.74483.1331   708.4  487.11
   744.3  493.37   824.1   500.4     868  509.21  895.51510.5766   915.9  516.16
  928.23 516.914  931.15517.0089   969.7 523.005   991.7  528.54  1043.6  529.41
  1111.4  536.93  1239.1   559.5 1318.79566.9374 1375.21570.9606  1494.4  575.29
#Mann= 11 ,-1 , 0
       0     .12       0  425.97     .04       0   433.2     .04       0
   560.8     .04       0  598.74     .12       0  895.51     .06       0
  928.23     .12       0  931.15     .06       0   969.7     .12       0
 1318.79    .016       0 1375.21     .12       0
Bank Sta=433.2,560.8
XS Rating Curve= 0 ,0
Exp/Cntr=0.3,0.1

Type RM Length L Ch R = 1 ,2946.2  ,451.3,450,446.2
XS GIS Cut Line= 3
     2299410.904       391552.22     2299767.645      391289.565
     2300574.083      390773.104
#Sta/Elev= 30
       0  733.31    63.9  683.67    95.8  661.22   135.7  634.96   171.6  614.39
   227.5   576.7   275.4  535.44   291.3  524.05   335.2  496.01  373.34478.2245
   395.1  473.54   403.1  472.37   494.9  473.66   506.8  475.56  516.77479.7914
   526.8  481.99   558.7  483.33   574.7  480.23   586.6  482.16   598.6  478.83
  616.32480.1209  618.14479.9525   638.5  484.06  719.39 486.589   881.9  502.78
  988.44523.2121  1077.4  542.23  1201.1  557.89 1398.47570.9503  1400.6  571.11
#Mann= 10 ,-1 , 0
       0     .12       0  373.34     .04       0   395.1     .04       0
   494.9     .04       0  516.77     .12       0  616.32     .04       0
  618.14     .12       0  719.39     .06       0  988.44     .12       0
 1398.47    .016       0
Bank Sta=395.1,494.9
XS Rating Curve= 0 ,0
Exp/Cntr=0.3,0.1

Type RM Length L Ch R = 1 ,2496.2  ,477.3,472.8,469.3
XS GIS Cut Line= 4
     2299747.159      391891.781      2300043.58      391644.974
     2300478.605       391248.99     2300628.679        390827.7
#Sta/Elev= 30
       0  709.14    67.6  671.48   135.2  627.82   202.8  576.77   230.6   547.2
   266.4  519.23   302.2  487.02  315.79480.0873   326.1     478     334  473.44
     342  471.74   453.3  471.75   461.2  474.92  474.45477.1635     505  481.83
   528.8  482.31   544.7  488.81   576.5  487.49   612.3  481.42  783.48488.7063
  794.81489.0204   842.8  494.73   866.7  506.38  903.78515.7722  962.22 526.374
  1041.9  535.13  1129.7  540.54  1273.5  556.94 1416.96567.2484  1421.2   567.4
#Mann= 10 ,-1 , 0
       0     .12       0  315.79     .04       0     334     .04       0
   461.2     .04       0  474.45     .12       0  783.48     .06       0
  794.81     .12       0  903.78     .06       0  962.22     .12       0
 1416.96    .016       0
Bank Sta=334,461.2
XS Rating Curve= 0 ,0
Exp/Cntr=0.3,0.1

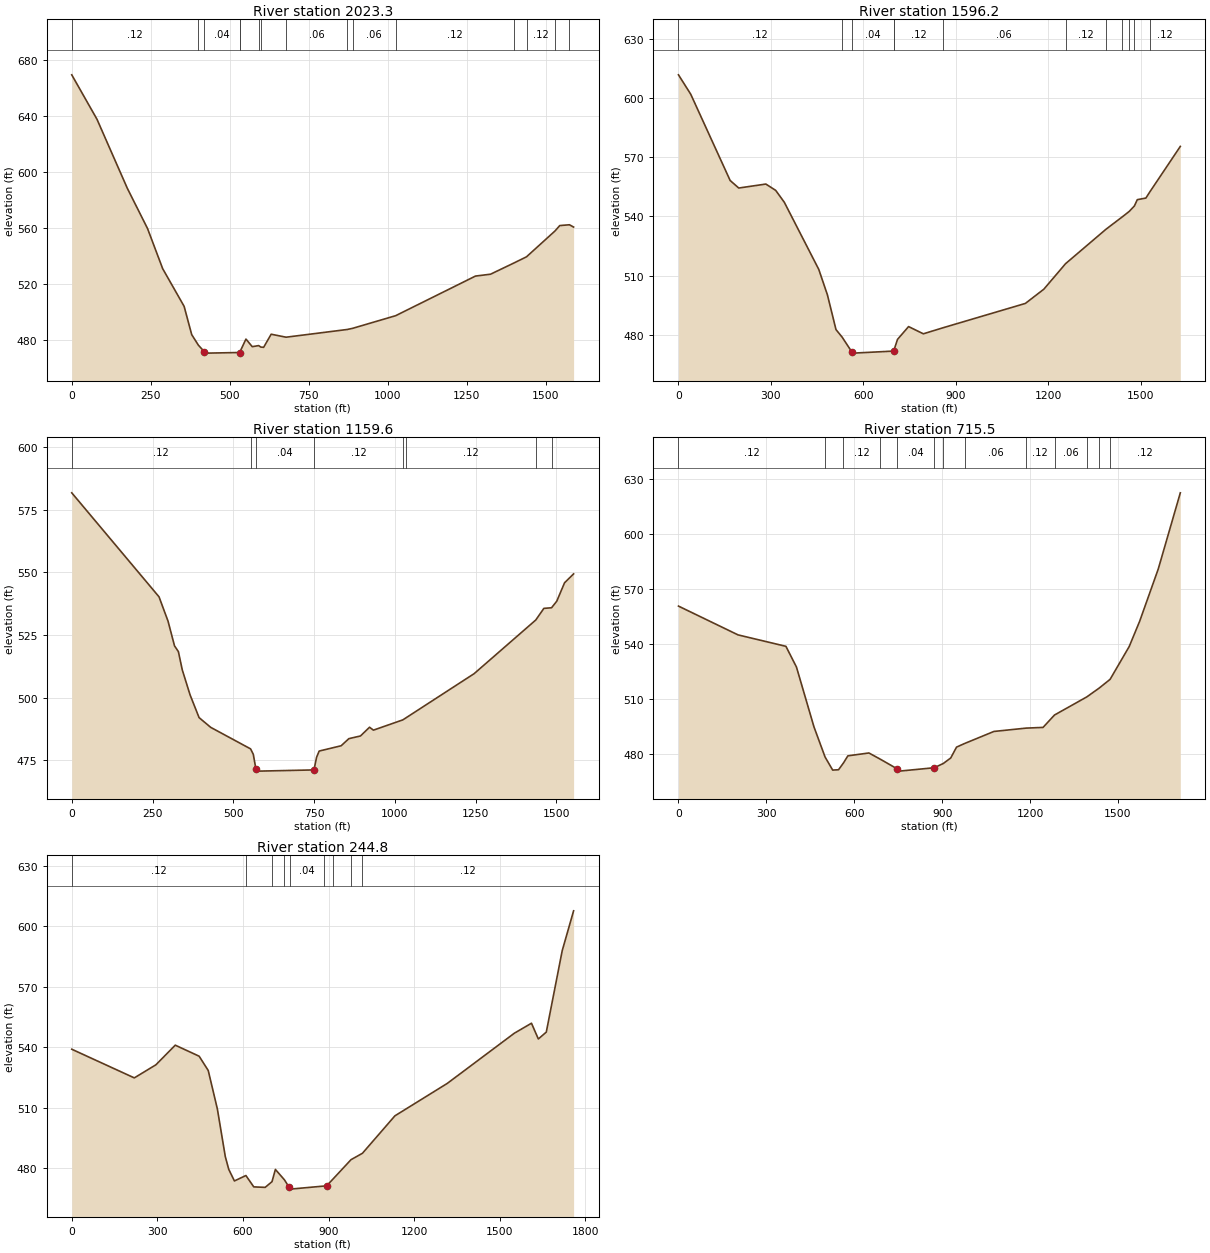
Type RM Length L Ch R = 1 ,2023.3  ,430.1,427.2,424.3
XS GIS Cut Line= 4
     2300184.525      392343.129     2300293.585      392081.148
     2300863.029       391365.87      2301095.94      391052.918
#Sta/Elev= 30
       0  669.61    79.9  637.83   175.9  588.49   239.8  559.77   287.8  531.05
   355.6  504.16   379.6  483.94  401.07 476.308   419.5  471.75   427.5  470.71
   531.3  471.15  531.41471.2061   551.3  480.75   571.2  475.32  591.52476.0904
  598.36475.0381   607.2  474.86   631.1  484.22   678.3482.0915  871.62487.6006
  889.44488.4652 1025.04497.4634  1277.7  525.78  1325.4  527.12 1400.14535.2104
 1439.16539.5451 1529.17557.9825  1544.4  561.87 1575.06562.4468  1588.2  560.81
#Mann= 15 ,-1 , 0
       0     .12       0  401.07     .04       0   419.5     .04       0
   531.3     .04       0  531.41     .12       0  591.52     .04       0
  598.36     .12       0   678.3     .06       0  871.62    .016       0
  889.44     .06       0 1025.04     .12       0 1400.14    .016       0
 1439.16     .12       0 1529.17    .016       0 1575.06     .12       0
Bank Sta=419.5,531.3
XS Rating Curve= 0 ,0
Exp/Cntr=0.3,0.1

Type RM Length L Ch R = 1 ,1596.2  ,433.9,436.6,439.4
XS GIS Cut Line= 3
     2300459.867      392666.878     2300781.067      392142.525
     2301310.432      391278.346
#Sta/Elev= 30
       0  611.73    39.9  601.86   167.7  558.18   195.6  554.37   283.5  556.38
   315.4  553.18   343.4  547.16   455.2  513.14   483.2  500.27   511.1  482.63
  531.22478.7657     563   471.2     567  470.71   698.7  471.75  700.86 473.019
   710.7  477.67   746.6  484.16   794.5   480.5   857.2483.5035  1125.6   495.9
  1185.5  503.11 1255.91516.0267 1387.07533.4746 1439.71539.7247 1462.55542.5225
 1479.26 545.274  1488.7  548.47  1516.6  549.29 1529.57552.4525  1628.3  575.46
#Mann= 12 ,-1 , 0
       0     .12       0  531.22     .04       0     563     .04       0
   698.7     .04       0  700.86     .12       0   857.2     .06       0
 1255.91     .12       0 1387.07     .06       0 1439.71    .016       0
 1462.55     .12       0 1479.26    .016       0 1529.57     .12       0
Bank Sta=563,698.7
XS Rating Curve= 0 ,0
Exp/Cntr=0.3,0.1

Type RM Length L Ch R = 1 ,1159.6  ,441.4,444.1,446.8
XS GIS Cut Line= 3
     2300643.421       392754.09     2300910.782      392677.701
     2301704.109      391679.709
#Sta/Elev= 30
       0  581.67   270.1   540.2     298  530.48     318  520.66     330  518.36
     342  511.09     366  501.17     394  492.05   429.9  488.17  553.41 479.577
   561.8  477.41   569.8  471.61   577.8  470.71   749.6  471.19   757.6  476.22
   765.6  478.71   833.6  480.82   857.6  483.66   893.5  484.73   921.5  488.21
   933.5  487.05 1024.32491.1323 1034.11491.9402  1245.2  509.57 1435.94530.9639
    1461   535.6  1484.7  535.84    1501  538.49    1525  545.81    1553  549.35
#Mann= 8 ,-1 , 0
       0     .12       0  553.41     .04       0   569.8     .04       0
   749.6     .12       0 1024.32     .06       0 1034.11     .12       0
 1435.94    .016       0  1484.7     .12       0
Bank Sta=569.8,749.6
XS Rating Curve= 0 ,0
Exp/Cntr=0.3,0.1

Type RM Length L Ch R = 1 ,715.5   ,467,470.7,474.4
XS GIS Cut Line= 4
     2300820.504      393038.812     2301163.242      392985.704
     2301903.837       392254.09     2302202.448      392125.618
#Sta/Elev= 30
       0  560.82   203.3   545.1   366.8  538.85   402.7  527.54   462.5  494.85
  500.39478.4073   526.3  471.28   546.3  471.46  563.12475.1622   578.2  479.06
     650  480.62  689.23477.1888   745.7  472.03   753.7  470.71   873.3  472.57
  904.26474.9229   929.2  477.88   949.1  483.82  976.42485.7792  1076.7  492.38
 1186.76494.1959  1244.3  494.58  1283.5501.3503 1393.69511.2362 1436.33516.0953
  1473.2520.8245  1538.5  538.76  1574.2  552.58  1637.6  581.08  1712.9  622.67
#Mann= 13 ,-1 , 0
       0     .12       0  500.39     .04       0  563.12     .12       0
  689.23     .04       0   745.7     .04       0   873.3     .04       0
  904.26     .12       0  976.42     .06       0 1186.76     .12       0
  1283.5     .06       0 1393.69     .12       0 1436.33    .016       0
  1473.2     .12       0
Bank Sta=745.7,873.3
XS Rating Curve= 0 ,0
Exp/Cntr=0.3,0.1

Type RM Length L Ch R = 1 ,244.8   ,243.7,244.8,245.9
XS GIS Cut Line= 3
     2301077.258      393496.913     2301499.717      393232.779
     2302528.543      392504.727
#Sta/Elev= 30
       0  538.95   219.2  524.72     295  531.23   362.7  540.96   446.4  535.48
   478.3  528.38   510.2  509.34   538.1  485.63   550.1  479.34     570  473.57
  610.24476.2615   637.8  470.63   677.7  470.38  701.75473.2211   713.6  479.28
  745.45474.0995  761.19  470.53   765.5  469.51   893.1  471.15  913.92474.2795
  978.52484.1169 1018.73487.3138  1132.4  505.88  1315.9  521.98  1551.2  546.92
    1611  551.85    1635  544.04  1662.9  547.44  1718.7  587.87  1758.6  607.64
#Mann= 9 ,-1 , 0
       0     .12       0  610.24     .04       0  701.75     .12       0
  745.45     .04       0   765.5     .04       0   885.1     .04       0
  913.92     .12       0  978.52    .016       0 1018.73     .12       0
Bank Sta=761.19,893.1
XS Rating Curve= 0 ,0
Exp/Cntr=0.3,0.1

Chan Stop Cuts=-1
Use User Specified Reach Order=0
Composite Channel Slope=5